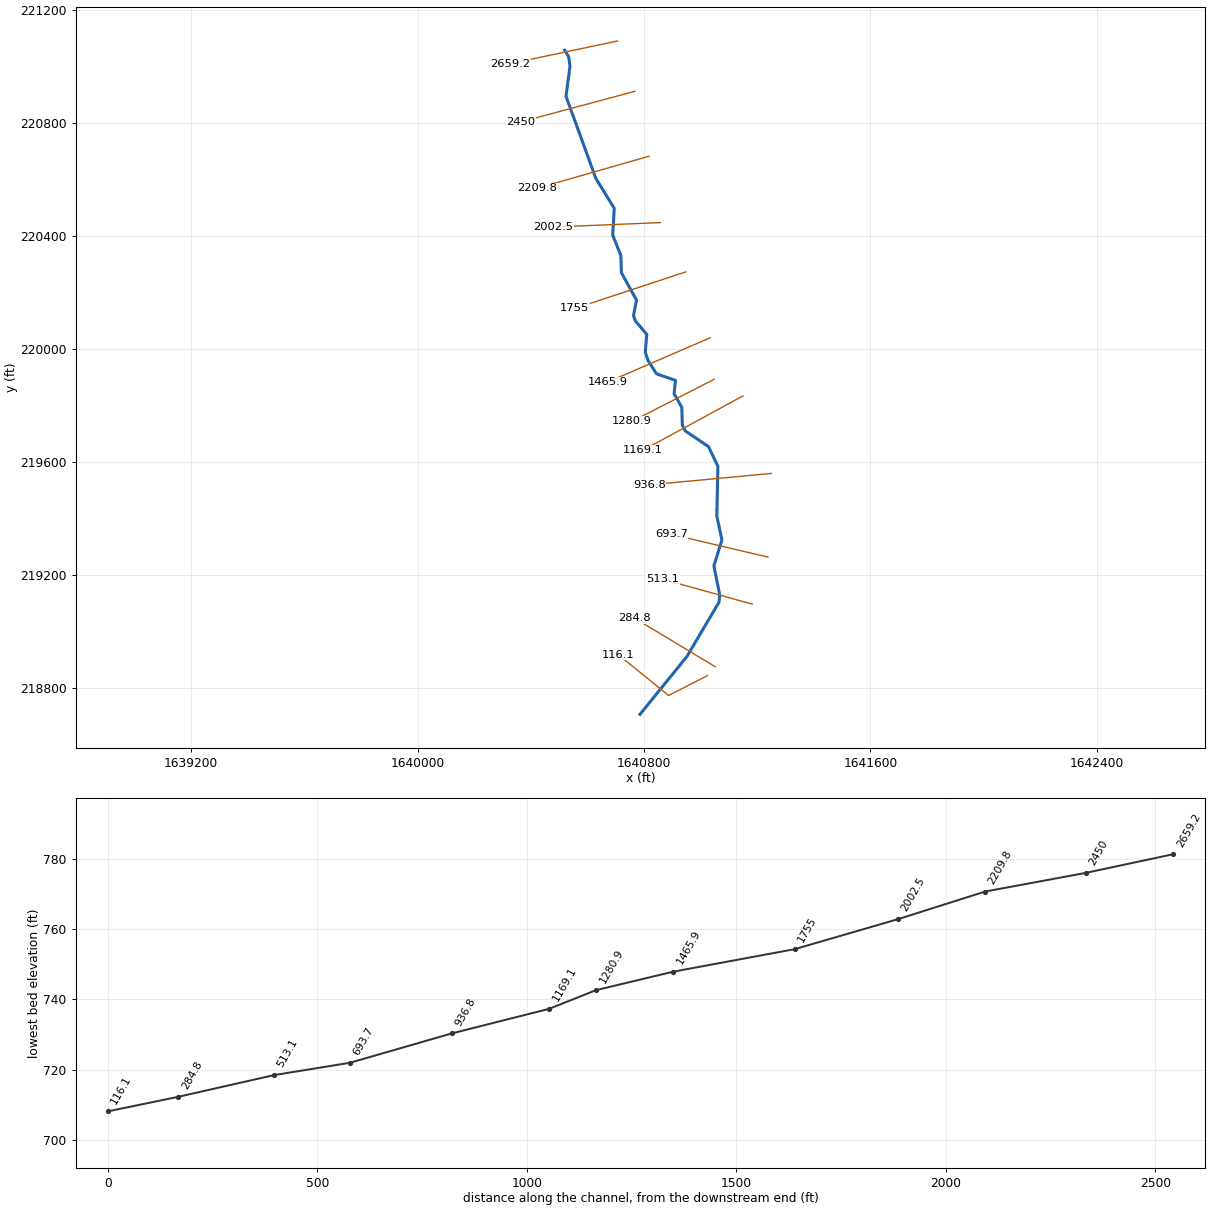
--- scssrsvllb.prj (project) ---

Proj Title=scssrsvllb
Current Plan=p01
Default Exp/Contr=0,0
English Units
Geom File=g01
Flow File=f01
Plan File=p01
BEGIN DESCRIPTION:
END DESCRIPTION:
DSS Export Rating Curves= 0
DSS Export Rating Curve Sorted= 0
DSS Export Volume Flow Curves= 0
DXF OffsetX= 0
DXF OffsetY= 0
DXF ScaleX= 0
DXF ScaleY= 0

--- scssrsvllb.p01 (plan) ---

Plan Title=Approximate Study  - 100yr
Program Version=4.00
Geom File=g01
Flow File=f01
Subcritical Flow
K Sum by GR= 0
Std Step Tol= 0.01
Critical Tol= 0.01
Num of Std Step Trials= 20
Max Error Tol= 0.3
Flow Tol Ratio= 0.001
Split Flow NTrial= 30
Split Flow Tol= 0.02
Split Flow Ratio= 0.02
Log Output Level= 0
Friction Slope Method= 1
Unsteady Friction Slope Method= 2
Unsteady Bridges Friction Slope Method= 1
Parabolic Critical Depth
Global Vel Dist= 0 , 0 , 0
Global Log Level= 0
CheckData=True
Encroach Param=-1 ,0,0, 0
Run HTab= 0
Run UNet= 0
Run PostProcess= 0
Run WQNet= 0
UNET Theta= 0
UNET Theta Warmup= 0
UNET ZTol= 0
UNET ZSATol= 0
UNET MxIter= 0
UNET MaxInSteps= 0
UNET DtIC= 0
UNET DtMin= 0
UNET MaxCRTS= 0
UNET WFStab= 0
UNET SFStab= 0
UNET WFX= 1
UNET SFX= 1
UNET DSS MLevel= 1
UNET DZMax Abort= 0
UNET Convert EG Bridges= 0
UNET Use Existing IB Tables= 0
UNET Froude Reduction=False
UNET Froude Limit= 0
UNET Froude Power= 0
UNET Time Slicing=0,0, 5
Write IC File= 0
Echo Input=False
Echo Output=False
Write Detailed= 0
Detailed Automatic Start=False, 0
WQ ULTIMATE=-1
WQ Max Comp Step=1HOUR
WQ Output Interval=15MIN
WQ Output Selected Increments= 0
WQ Output face flow=0
WQ Output face velocity=0
WQ Output face area=0
WQ Output face dispersion=0
WQ Output cell volume=0
WQ Output cell surface area=0
WQ Output cell continuity=0
WQ Output face conc=0
WQ Output face dconc_dx=0
WQ Output face courant=0
WQ Output face peclet=0
WQ Output face adv mass=0
WQ Output face disp mass=0
WQ Output cell mass=0
WQ Output cell source sink temp=0
WQ Output cell source sink nsm=0
WQ Output MaxMinRange=-1
WQ Daily Max Min Mean=-1
WQ Daily Range=0
WQ Daily Time=0
WQ Create Restart=0
WQ Fixed Restart=0
WQ System Summary=False
Sorting and Armoring Iterations= 10
XS Update Threshold= 0.02
Hydraulics Update Threshold= 0.02
Energy Slope Method= 1
Volume Change Method= 0
XS Weighting Method= 0
Number of US Weighted Cross Sections= 1
Number of DS Weighted Cross Sections= 1
Upstream XS Weight=0.25
Main XS Weight=0.5
Downstream XS Weight=0.25
Number of DS XS's Weighted with US Boundary= 1
Upstream Boundary Weight= 1
Weight of XSs Associated with US Boundary= 0
Number of US XS's Weighted with DS Boundary= 1
Downstream Boundary Weight= 0.5
Weight of XSs Associated with DS Boundary= 0.5
Sediment Output Level= 4
Mass or Volume Output= 0
Output Increment Type= 1
Profile and TS Output Increment= 10
XS Output Flag= 0
XS Output Increment= 10
Disregard all LS=0
Disregard all Conn=0
Disregard all Breaches=0
Disregard all Pumps=0

--- scssrsvllb.f01 (steady flow) ---

Flow Title=USGS Regression Equation
Program Version=4.00
Number of Profiles= 1
Profile Names=P100yr
River Rch & RM=scssrsvllb,Main            ,2659.2
     430
River Rch & RM=scssrsvllb,Main            ,284.8
     452
Boundary for River Rch & Prof#=scssrsvllb,Main            , 1
Up Type= 0
Dn Type= 3
Dn Slope=0.017762
DSS Import GetInterval= 0
DSS Import GetPeak= 0
DSS Import FillOption= 0

--- scssrsvllb.g01 (geometry) ---

Geom Title=USGS 3m DEM
Program Version=4.00

River Reach=scssrsvllb      ,Main
Reach XY= 30
     1640519.729      221056.212     1640533.871      221033.025
      1640538.41      220999.089     1640524.343      220893.162
     1640629.689      220602.638     1640694.936      220496.598
     1640689.403      220401.433     1640718.205      220329.719
     1640720.083       220268.71     1640773.543      220171.849
     1640763.061      220116.913     1640769.053      220098.465
     1640809.992      220050.166     1640804.553      219986.561
     1640814.259      219957.995     1640843.944      219910.872
     1640911.414      219887.278      1640906.33      219840.823
      1640933.61      219791.592     1640935.555       219728.08
     1640946.482      219707.985       1641027.9      219653.088
     1641061.194      219583.211     1641057.305       219407.75
     1641075.456      219322.858     1641047.083      219230.719
     1641067.693      219128.337      1641065.04      219101.997
     1640951.659      218909.986     1640785.782      218705.133

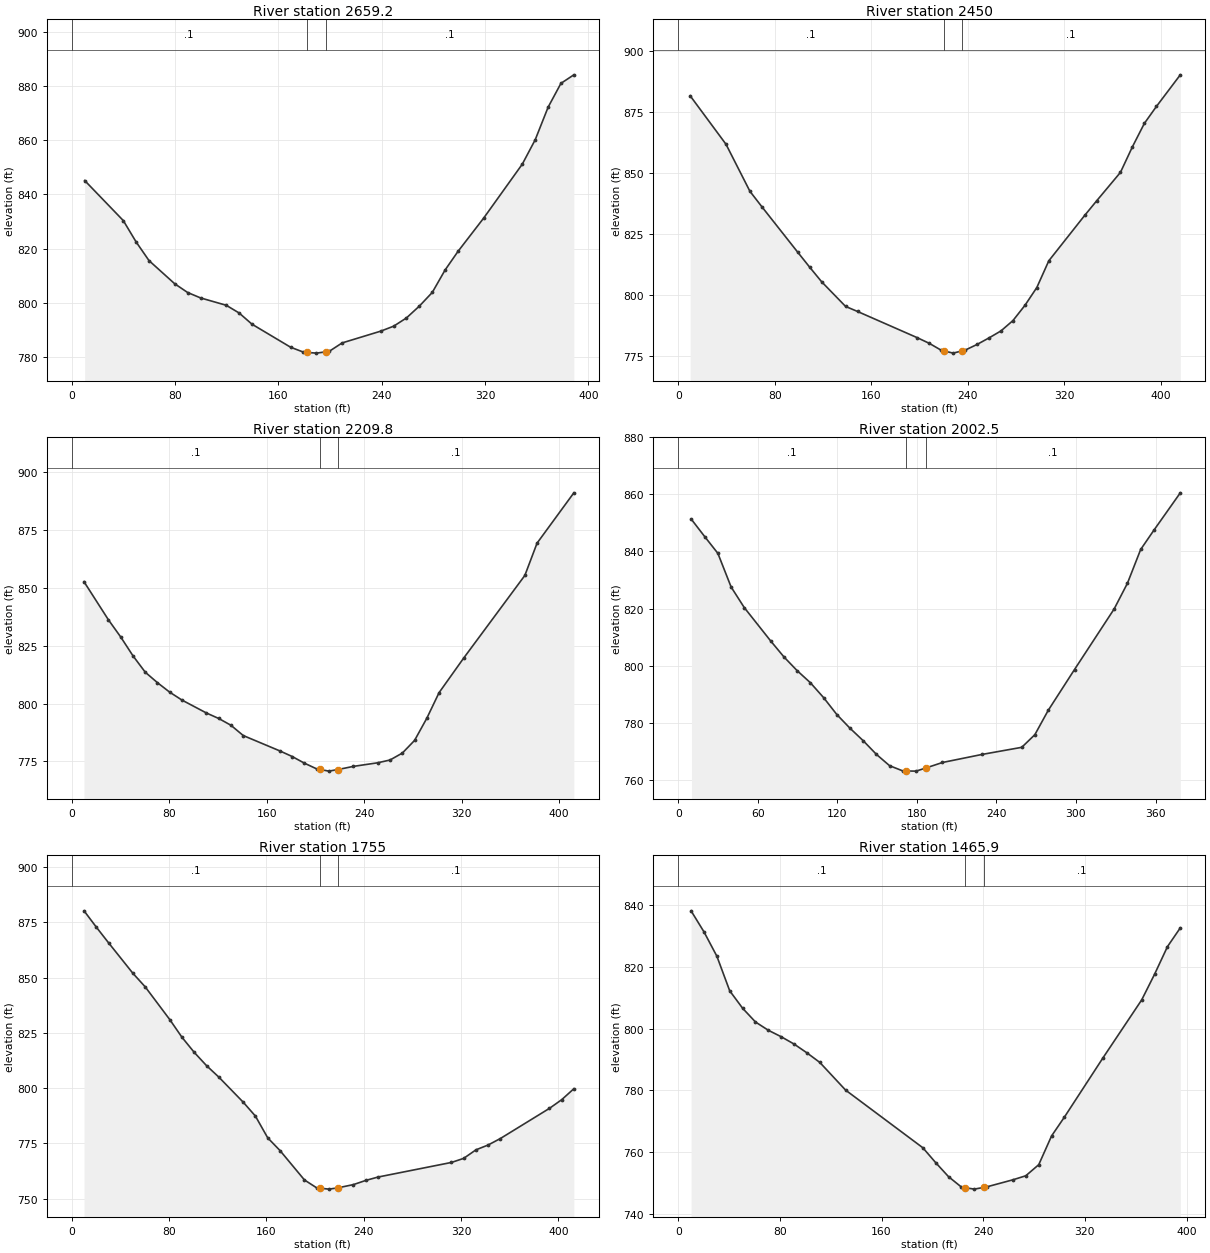
Type RM Length L Ch R = 1 ,2659.2  ,207.7,209.2,210.7
XS GIS Cut Line= 2
     1640706.686      221088.888     1640326.397      221008.518
#Sta/Elev= 30
      10   845.1    39.9  830.33    49.8  822.48    59.8  815.59    79.7  807.05
    89.7  803.83    99.7  801.84   119.6  799.12   129.6  796.27   139.5  792.16
   169.4  783.67   179.4  781.85   181.9  781.76   189.4  781.49   196.9  781.98
   199.3  782.14   209.3  785.25   239.2  789.59   249.2  791.42   259.1  794.45
   269.1  798.82   279.1  803.86     289  812.11     299  818.97   318.9  831.26
   348.8  851.14   358.8  860.13   368.8  872.14   378.7   880.9   388.7  884.05
#Mann= 3 , 0 , 0
       0      .1       0   181.9    .045       0   196.9      .1       0
Bank Sta=181.9,196.9
XS Rating Curve= 0 ,0
Exp/Cntr=0.3,0.1

Type RM Length L Ch R = 1 ,2450    ,239.7,240.1,240.6
XS GIS Cut Line= 2
     1640767.454      220910.505     1640365.602      220802.691
#Sta/Elev= 30
     9.9  881.67    39.6  861.79    59.4  842.52    69.3  836.18    99.1  817.49
     109  811.35   118.9  805.38   138.7   795.3   148.6  793.23   198.1  782.48
     208  780.18   217.9  777.35   220.3  777.06   227.8  776.15   235.3  777.07
   237.8  777.38   247.7  779.72   257.6   782.4   267.5  785.27   277.4   789.5
   287.3  795.72   297.2  803.06   307.1     814   336.8  832.59   346.7  838.56
   366.5  850.28   376.4  860.75   386.3  870.35   396.3   877.3   416.1  890.27
#Mann= 3 , 0 , 0
       0      .1       0   220.3    .045       0   235.3      .1       0
Bank Sta=220.3,235.3
XS Rating Curve= 0 ,0
Exp/Cntr=0.3,0.1

Type RM Length L Ch R = 1 ,2209.8  ,212.8,207.3,201.9
XS GIS Cut Line= 2
      1640818.42      220681.156      1640422.45      220567.461
#Sta/Elev= 30
      10  852.76    30.1  836.23    40.2   828.8    50.2   820.7    60.3   813.6
    70.3  809.07    80.4  804.95    90.4  801.55   110.5  795.96   120.6  793.58
   130.6  790.66   140.7  786.21   170.8  779.55   180.9  777.13   190.9  774.26
     201  771.79   203.5  771.55     211  770.82   218.5  771.51   231.1  772.87
   251.2  774.44   261.2  775.64   271.3  778.64   281.3   784.1   291.4  793.74
   301.4  804.75   321.5  819.63   371.8  855.44   381.8  869.39     412  891.16
#Mann= 3 , 0 , 0
       0      .1       0   203.5    .045       0   218.5      .1       0
Bank Sta=203.5,218.5
XS Rating Curve= 0 ,0
Exp/Cntr=0.3,0.1

Type RM Length L Ch R = 1 ,2002.5  ,241.3,247.5,253.7
XS GIS Cut Line= 2
     1640857.625      220445.926     1640479.297      220430.244
#Sta/Elev= 30
      10  851.24    19.9  845.26    29.9  839.35    39.9  827.54    49.8  820.33
    69.8  808.58    79.7  803.04    89.7   798.2    99.6     794   109.6  788.77
   119.6  782.82   129.5  778.03   139.5  773.64   149.5  768.83   159.4  764.87
   169.4  763.03   171.9  763.01   179.4  762.96   186.9  764.08   199.3  765.99
   229.2  768.82   259.1  771.31     269  775.75     279  784.23   298.9   798.6
   328.8  819.85   338.8  828.84   348.8  840.71   358.7  847.42   378.7  860.58
#Mann= 3 , 0 , 0
       0      .1       0   171.9    .045       0   186.9      .1       0
Bank Sta=171.9,186.9
XS Rating Curve= 0 ,0
Exp/Cntr=0.3,0.1

Type RM Length L Ch R = 1 ,1755    ,286.9,289.1,291.2
XS GIS Cut Line= 2
     1640947.797      220271.464     1640555.747      220142.087
#Sta/Elev= 30
    10.1  880.19    20.1  872.88    30.2  865.77    50.3  851.92    60.4   845.8
    80.6     831    90.6  823.02   100.7  816.19   110.8  810.19   120.8  805.07
     141  793.65     151  787.38   161.1  777.55   171.2  771.81   191.3  758.51
   201.4  754.93     204  754.78   211.5  754.36     219  754.96   231.6  756.41
   241.7  758.29   251.7  759.81   312.2  766.43   322.2  768.26   332.3  772.12
   342.4  774.33   352.4  777.24   392.7  790.86   402.8  794.79   412.8  799.75
#Mann= 3 , 0 , 0
       0      .1       0     204    .045       0     219      .1       0
Bank Sta=204,219
XS Rating Curve= 0 ,0
Exp/Cntr=0.3,0.1

Type RM Length L Ch R = 1 ,1465.9  ,183.9,185,184.3
XS GIS Cut Line= 2
     1641034.048      220038.194     1640671.402      219881.374
#Sta/Elev= 30
    10.1  838.19    20.3  831.34    30.4  823.48    40.5  812.26    50.7  806.58
    60.8  802.14    70.9  799.46      81  797.37    91.2  794.98   101.3  792.13
   111.4  789.04   131.7  780.06   192.5  761.36   202.6  756.54   212.7  751.99
   222.9   748.6   225.5  748.44     233  747.95   240.5  748.52   243.1  748.72
   263.4  750.98   273.5  752.28   283.7  755.88   293.8   765.2   303.9  771.31
   334.3  790.55   364.7   809.3   374.8  817.59     385  826.59   395.1  832.67
#Mann= 3 , 0 , 0
       0      .1       0   225.5    .045       0   240.5      .1       0
Bank Sta=225.5,240.5
XS Rating Curve= 0 ,0
Exp/Cntr=0.3,0.1

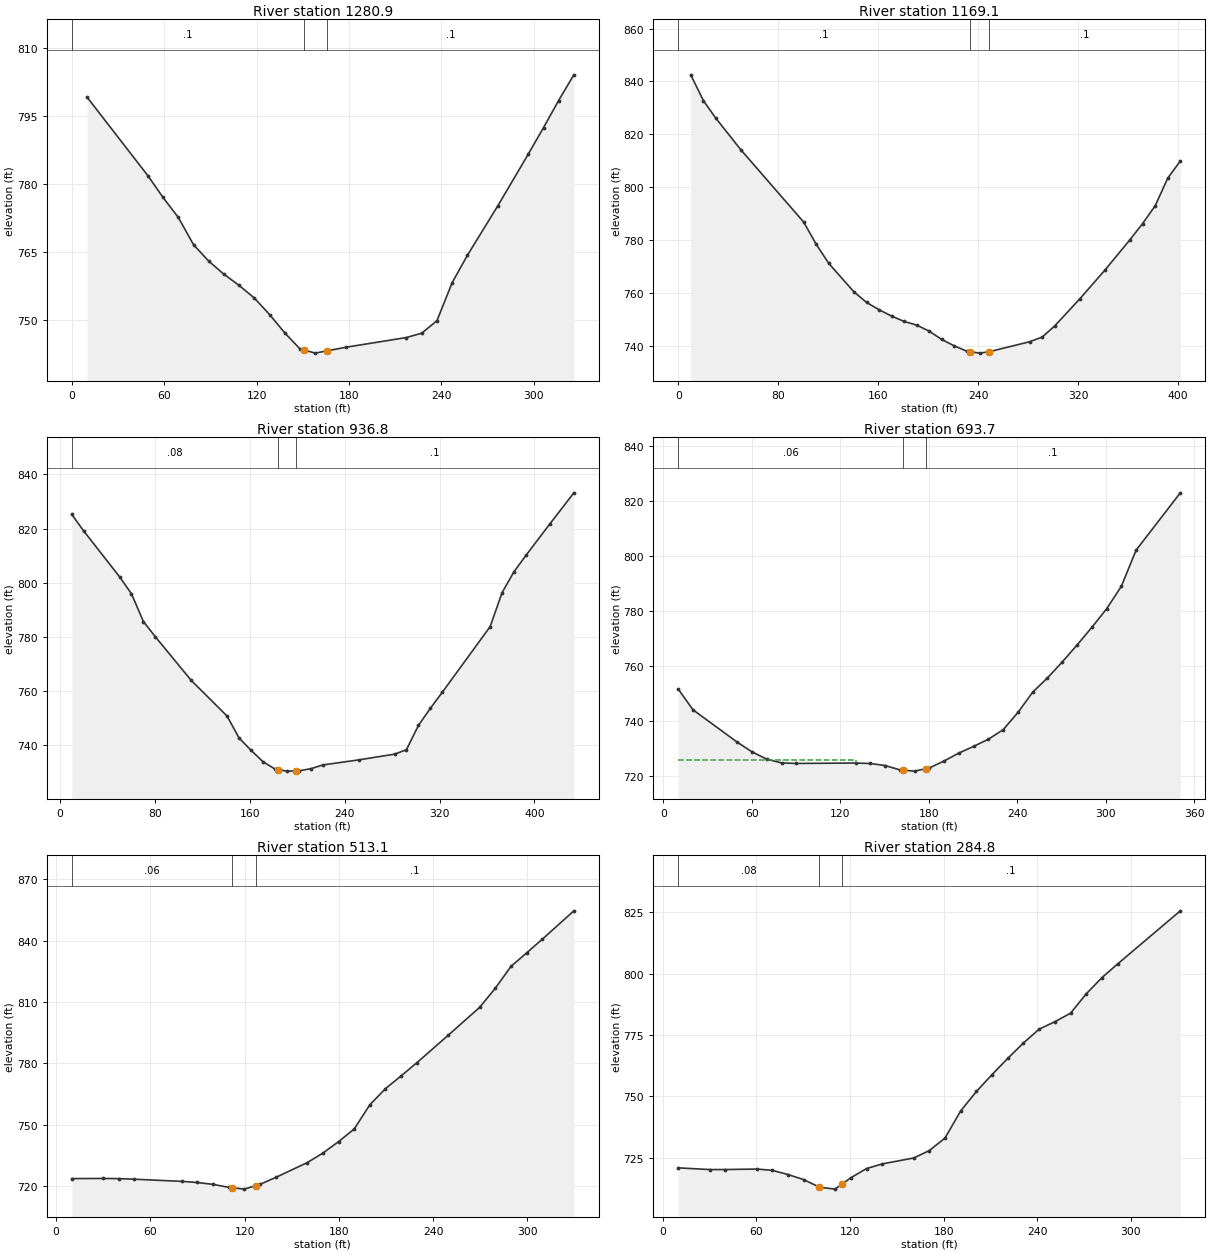
Type RM Length L Ch R = 1 ,1280.9  ,111.3,111.8,112.3
XS GIS Cut Line= 2
      1641047.77      219891.175     1640757.653      219742.196
#Sta/Elev= 26
     9.9  799.09    49.4  781.78    59.3  776.96    69.2  772.56    79.1  766.55
    88.9  762.95    98.8  760.05   108.7  757.58   118.6  754.79   128.5  751.15
   138.4  747.09   148.2   743.6   150.6  743.37   158.1  742.65   165.6  743.14
   177.9  743.94   217.4  746.09   227.3  747.05   237.2  749.81   247.1  758.21
     257  764.24   276.7  775.11   296.5  786.52   306.4  792.36   316.2  798.33
   326.1     804
#Mann= 3 , 0 , 0
       0      .1       0   150.6    .045       0   165.6      .1       0
Bank Sta=150.6,165.6
XS Rating Curve= 0 ,0
Exp/Cntr=0.3,0.1

Type RM Length L Ch R = 1 ,1169.1  ,241.3,232.3,223.4
XS GIS Cut Line= 2
     1641149.702      219832.368     1640796.858      219640.263
#Sta/Elev= 30
      10  842.52    20.1  832.79    30.1  826.11    50.2  814.14   100.4  786.85
   110.5   778.4   120.5  771.23   140.6  760.49   150.7  756.49   160.7  753.73
   170.7  751.33   180.8   749.3   190.8  747.92   200.9  745.61   210.9  742.48
     221  740.04     231  738.05   233.6  737.86   241.1  737.32   248.6  737.82
   281.2  741.62   291.3  743.39   301.3  747.61   321.4  757.86   341.5  768.73
   361.6  780.24   371.6  786.27   381.7  793.03   391.7  803.42   401.8  809.95
#Mann= 3 , 0 , 0
       0      .1       0   233.6    .045       0   248.6      .1       0
Bank Sta=233.6,248.6
XS Rating Curve= 0 ,0
Exp/Cntr=0.3,0.1

Type RM Length L Ch R = 1 ,936.8   ,250.4,243.1,235.8
XS GIS Cut Line= 2
     1641249.675      219557.932     1640818.387      219517.534
#Sta/Elev= 30
    10.1  825.23    20.1  819.14    50.4  802.16    60.4  795.88    70.5  785.59
    80.6  779.95   110.8  763.83     141  750.65   151.1  742.54   161.2     738
   171.3  733.76   181.3   731.1   183.9  730.89   191.4   730.3   198.9  730.39
   201.5  730.42   211.6   731.2   221.6  732.58   251.8  734.45   282.1  736.58
   292.1  738.21   302.2  747.18   312.3  753.54   322.4  759.49   362.7  783.76
   372.7  796.29   382.8  804.06   392.9  810.12     413  821.73   433.2  833.21
#Mann= 3 , 0 , 0
    10.1     .08       0   183.9    .045       0   198.9      .1       0
Bank Sta=183.9,198.9
XS Rating Curve= 0 ,0
Exp/Cntr=0.3,0.1

Type RM Length L Ch R = 1 ,693.7   ,181.7,180.6,179
XS GIS Cut Line= 2
     1641237.914      219261.935      1640896.83      219342.305
#Sta/Elev= 30
      10   751.7      20  744.17    50.1  732.39    60.1  728.89    70.1  726.24
    80.1   724.9    90.1  724.71   130.2  724.86   140.2  724.69   150.2  723.96
   160.2  722.39   162.7  722.27   170.2  721.92   177.7  722.78   180.2  723.07
   190.2  725.59   200.2  728.46   210.3  730.91   220.3  733.51   230.3  736.95
   240.3   743.2   250.3  750.57   260.3  755.73   270.3  761.49   280.3  767.63
   290.4  774.08   300.4  780.81   310.4  788.96   320.4   802.1   350.4  822.92
#Mann= 3 , 0 , 0
      10     .06       0   162.7    .045       0   177.7      .1       0
#XS Ineff= 2 , 0
       0   130.2     726               0
Permanent Ineff=
       F       F
Bank Sta=162.7,177.7
XS Rating Curve= 0 ,0
Exp/Cntr=0.3,0.1

Type RM Length L Ch R = 1 ,513.1   ,234.3,228.3,222.9
XS GIS Cut Line= 2
     1641183.027      219095.313     1640865.466      219183.525
#Sta/Elev= 28
      10  723.56      30  723.63    39.9  723.55    49.9  723.27    79.9  722.21
    89.9  721.66    99.9  720.73   109.9   719.3   112.3  719.09   119.8  718.41
   127.3  720.15   129.8  720.74   139.8  724.12   159.8  731.35   169.8  736.02
   179.8  741.65   189.8  747.85   199.7  759.68   209.7  767.61   219.7  773.86
   229.7  780.31   249.7  793.77   269.7  807.44   279.6  816.73   289.6  827.46
   299.6  834.07   309.6   840.8   329.6  854.63
#Mann= 3 , 0 , 0
      10     .06       0   112.3    .045       0   127.3      .1       0
Bank Sta=112.3,127.3
XS Rating Curve= 0 ,0
Exp/Cntr=0.3,0.1

Type RM Length L Ch R = 1 ,284.8   ,171.8,168.7,165.5
XS GIS Cut Line= 2
      1641051.69      218873.805     1640767.665      219045.006
#Sta/Elev= 29
      10  720.89    30.1  720.19    40.2   720.2    60.3   720.4    70.3  719.87
    80.4  718.15    90.4  716.08     100 713.143   100.5  712.99   110.5  712.22
     115 714.296   120.6  716.87   130.6   720.6   140.7   722.5   160.8   724.9
   170.8  727.92   180.9  733.04   190.9  744.08     201  752.01     211  758.89
   221.1  765.51   231.1  771.75   241.2   777.4   251.2  780.41   261.3   783.9
   271.3  791.76   281.4   798.4   291.4  803.94   331.6   825.6
#Mann= 3 , 0 , 0
      10     .08       0     100    .045       0     115      .1       0
Bank Sta=100,115
XS Rating Curve= 0 ,0
Exp/Cntr=0.3,0.1

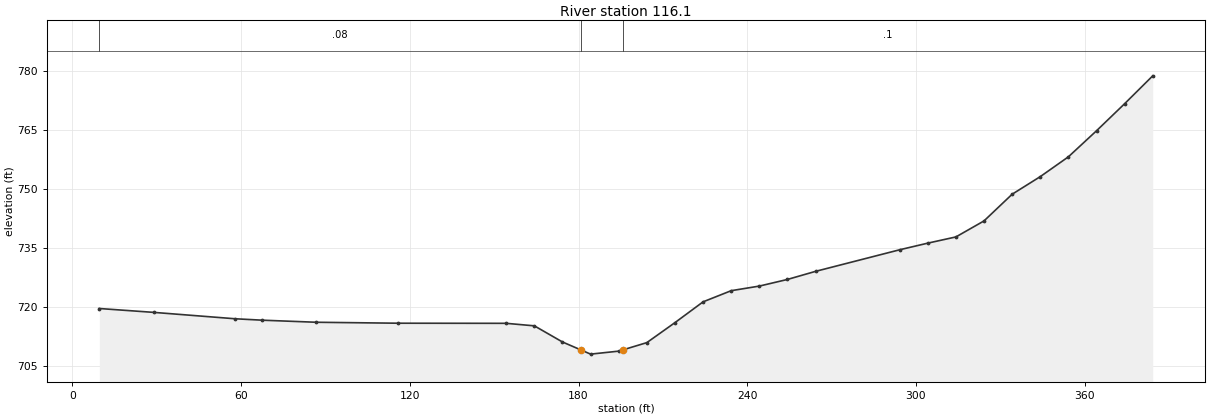
Type RM Length L Ch R = 1 ,116.1   ,110.6,116.1,127.9
XS GIS Cut Line= 3
     1641024.246      218842.441     1640887.029      218771.872
     1640708.646      218916.931
#Sta/Elev= 30
     9.6  719.66    28.9  718.68    57.9  717.05    67.5  716.69    86.8  716.16
   115.7  715.92   154.3  715.89   164.3  715.25   174.3  711.14   180.8 709.133
   184.3  708.05   194.3  708.81   195.8 709.136   204.3  710.98   214.3  716.07
   224.3  721.36   234.3   724.2   244.3  725.37   254.3  727.06   264.3  729.12
   294.3  734.63   304.2   736.3   314.2  737.88   324.2  741.96   334.2  748.75
   344.2  753.23   354.2  758.27   364.2   764.9   374.2  771.79   384.2  778.89
#Mann= 3 , 0 , 0
     9.6     .08       0   180.8    .045       0   195.8      .1       0
Bank Sta=180.8,195.8
XS Rating Curve= 0 ,0
Exp/Cntr=0.3,0.1

Chan Stop Cuts=-1
Use User Specified Reach Order=0